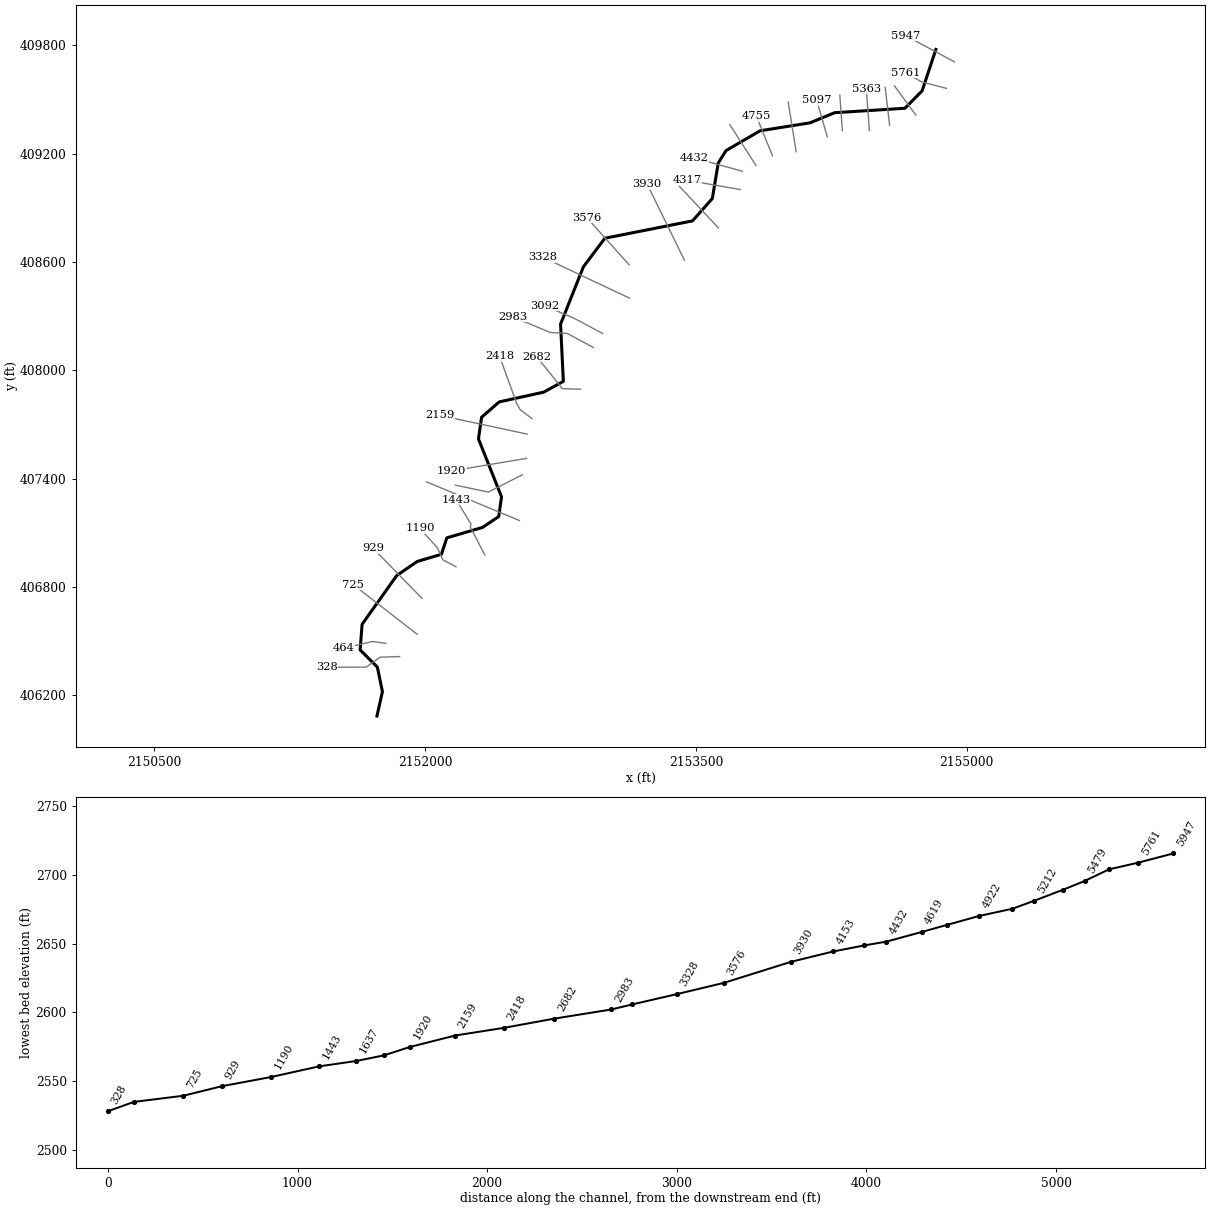
--- RBBNSRN.prj (project) ---

Proj Title=RBBNSRN
Current Plan=p01
Default Exp/Contr=0,0
English Units
Geom File=g01
Flow File=f01
Plan File=p01
Background Map Layer=Inundation Boundary (01pct Value_0)
BEGIN DESCRIPTION:
----------MODEL BY WOOD PLC 2021----------
Stream Name: Robbins Run
Flood Zone: Enhanced Approximate
Pocahontas County, WV
HEC-RAS Version: RAS 6.1
Vertical Datum: NAVD88
Projection: NAD 1983 StatePlane West Virginia S FIPS 4702 (US Feet)
Terrain: 1-meter LIDAR (FEMA Region III 3DEP collected 2016-2018)
Land Use: 2019 NLCD
Hydrologic Method:
WV SIR2010-5033 regression equations
Model Notes:
KWSEL at county boundary
END DESCRIPTION:
DSS File=dss
DSS Export Rating Curves= 0
DSS Export Rating Curve Sorted= 0
DSS Export Volume Flow Curves= 0
DXF OffsetX= 0
DXF OffsetY= 0
DXF ScaleX= 0
DXF ScaleY= 0

--- RBBNSRN.p01 (plan) ---

Plan Title=Floodplain
Program Version=6.00
Short Identifier=Floodplain
Geom File=g01
Flow File=f01
Subcritical Flow
K Sum by GR= 0
Std Step Tol= 0.01
Critical Tol= 0.01
Num of Std Step Trials= 20
Max Error Tol= 0.3
Flow Tol Ratio= 0.001
Split Flow NTrial= 30
Split Flow Tol= 0.02
Split Flow Ratio= 0.02
Log Output Level= 0
Friction Slope Method= 1
Unsteady Friction Slope Method= 2
Unsteady Bridges Friction Slope Method= 1
Parabolic Critical Depth
Global Vel Dist= 0 , 0 , 0
Global Log Level= 0
CheckData=True
Encroach Param=-1 ,0,0, 0
Computation Interval=0.1SEC
Output Interval=1SEC
Instantaneous Interval=Max Profile
Mapping Interval=1HOUR
Computation Time Step Use Courant=        0
Computation Time Step Use Time Series=    0
Computation Time Step Count To Double=0
Computation Time Step Max Doubling=0
Computation Time Step Max Halving=0
Computation Time Step Residence Courant=0
Run HTab= 0
Run UNet= 0
Run Sediment= 0
Run PostProcess= 0
Run WQNet= 0
Run RASMapper=-1
UNET Theta= 0
UNET Theta Warmup= 0
UNET ZTol= 0
UNET ZSATol= 0
UNET MxIter= 0
UNET Max Iter WO Improvement= 0
UNET MaxInSteps= 0
UNET DtIC= 0
UNET DtMin= 0
UNET MaxCRTS= 0
UNET WFStab= 0
UNET SFStab= 0
UNET WFX= 1
UNET SFX= 1
UNET Gravity=32.174
UNET 1D Methodology=Finite Difference
UNET DSS MLevel= 1
UNET Pardiso=0
UNET DZMax Abort= 0
UNET Use Existing IB Tables= 0
UNET Froude Reduction=False
UNET Froude Limit= 0
UNET Froude Power= 0
UNET D1 Cores= 0
UNET WindReference=Eulerian
UNET WindDragFormulation=Hsu (1988)
UNET D2 Coriolis=0
UNET D2 Cores= 0
UNET D2 Theta= 1
UNET D2 Theta Warmup= 1
UNET D2 Z Tol= 0.01
UNET D2 Volume Tol= 0.01
UNET D2 Max Iterations= 20
UNET D2 Equation= 0
UNET D2 RampUpFraction=0.1
UNET D2 TimeSlices= 1
UNET D2 Turbulence Formulation=Non-Conservative (original)
UNET D2 Eddy Viscosity=0.3
UNET D2 Transverse Eddy Viscosity=0.1
UNET D2 Smagorinsky Mixing=0
UNET D2 BCVolumeCheck=0
UNET D2 Cores=0
UNET D2 SolverType=PARDISO (Direct)
UNET D2 Minimum Iterations= 2147483647
UNET D2 Maximum Iterations= 2147483647
UNET D2 Restart Number= 10
UNET D2 Relaxation Coeff=1.3
UNET D2 SOR Precondition Iterations= 10
UNET D2 ILUT Maximum Fill= 8
UNET D2 ILUT Tolerance=1E-08
UNET D1D2 MaxIter= 0
UNET D1D2 ZTol=0.01
UNET D1D2 QTol=0.1
UNET D1D2 MinQTol=1
DSS File=dss
Write IC File= 0
Write IC File at Fixed DateTime=0
Write IC File at Sim End=0
Echo Input=False
Echo Parameters=False
Echo Output=False
Write Detailed= 0
HDF Write Warmup=0
HDF Write Time Slices=0
HDF Flush=0
HDF Compression= 1
HDF Chunk Size= 1
HDF Spatial Parts= 1
HDF Use Max Rows=0
HDF Fixed Rows= 1
Calibration Method= 0
Calibration Iterations= 20
Calibration Max Change=0.05
Calibration Tolerance=0.2
Calibration Maximum=1.5
Calibration Minimum=0.5
Calibration Optimization Method= 1
WQ AD Non Conservative
WQ ULTIMATE=-1
WQ Max Comp Step=1HOUR
WQ Output Interval=15MIN
WQ Output Selected Increments= 0
WQ Output face flow=0
WQ Output face velocity=0
WQ Output face area=0
WQ Output face dispersion=0
WQ Output cell volume=0
WQ Output cell surface area=0
WQ Output cell continuity=0
WQ Output cumulative cell continuity=0
WQ Output face conc=0
WQ Output face dconc_dx=0
WQ Output face courant=0
WQ Output face peclet=0
WQ Output face adv mass=0
WQ Output face disp mass=0
WQ Output cell mass=0
WQ Output cell source sink temp=0
WQ Output nsm pathways=0
WQ Output nsm derived pathways=0
WQ Create Restart=0
WQ Fixed Restart=0
WQ System Summary=0
WQ Write To DSS=0
Sorting and Armoring Iterations= 10
XS Update Threshold= 0.02
Bed Roughness Predictor= 0
Hydraulics Update Threshold= 0.02
Energy Slope Method= 1
Volume Change Method= 1
Sediment Retention Method= 0
Sediment TS Multiplier= 1
Warm Up Method= 0
XS Weighting Method= 0
Number of US Weighted Cross Sections= 1
Number of DS Weighted Cross Sections= 1
Upstream XS Weight=0
Main XS Weight=1
Downstream XS Weight=0
Number of DS XS's Weighted with US Boundary= 1
Upstream Boundary Weight= 1
Weight of XSs Associated with US Boundary= 0
Number of US XS's Weighted with DS Boundary= 1
Downstream Boundary Weight= 0.5
Weight of XSs Associated with DS Boundary= 0.5
Percentile Method= 0
Sediment Output Level= 3
Mass or Volume Output= 0
Output Increment Type= 1
Profile and TS Output Increment= 1
Transport Output Increment 1
XS Output Flag= 0
XS Output Increment= 10
Read HDF5 Sediment Hotstart= 0
Sediment Hotstart Type= 0
Write Gradation File= 0
Read Gradation Hotstart= 0
Write HDF5 File= 1
Write Binary Output= 1
Write DSS Sediment File= 0
DSS Sediment Output Type= 1
SV Curve= 0
Specific Gage Flag= 0
Subcell Erosion Methods= 0
Subcell Deposition Methods= 0
Advection Scheme= 1
Matrix Solver= 0
Implicit Weighting Factor= 1
Maximum Outer Loop Convergence Iterations= 5
Convergence Maximum Absolute= 0.001
Convergence RMSE= 0.0001
Grain Fractions Max Abs Error= 0.001
Max Subgrid Regions= 1
Max Subgrid Length Scale= 3.402823E+38
Initial Layer Thickness= 3.402823E+38
Min Layer Thickness= 3.402823E+38
Max Layer Thickness= 3.402823E+38
Number of Layers= 5

--- RBBNSRN.f01 (steady flow) ---

Flow Title=Flow
Program Version=6.00
Number of Profiles= 6
Profile Names=01pct,10pct,04pct,02pct,0_2pct,01plus
River Rch & RM=RBBNSRN,Main            ,5947
     909     489     644     772    1260    1340
River Rch & RM=RBBNSRN,Main            ,464
    1170     638     837    1000    1620    1740
Boundary for River Rch & Prof#=RBBNSRN,Main            , 1
Up Type= 0
Dn Type= 1
Dn Known WS=2524.1
Boundary for River Rch & Prof#=RBBNSRN,Main            , 2
Up Type= 0
Dn Type= 1
Dn Known WS=2523
Boundary for River Rch & Prof#=RBBNSRN,Main            , 3
Up Type= 0
Dn Type= 1
Dn Known WS=2523.5
Boundary for River Rch & Prof#=RBBNSRN,Main            , 4
Up Type= 0
Dn Type= 1
Dn Known WS=2523.8
Boundary for River Rch & Prof#=RBBNSRN,Main            , 5
Up Type= 0
Dn Type= 1
Dn Known WS=2524.9
Boundary for River Rch & Prof#=RBBNSRN,Main            , 6
Up Type= 0
Dn Type= 1
Dn Known WS=2525.1
DSS Import GetInterval= 0
DSS Import GetPeak= 0
DSS Import FillOption= 0

--- RBBNSRN.g01 (geometry) ---

Geom Title=Geometry
Program Version=6.10

River Reach=RBBNSRN         ,Main
Reach XY= 30
2154828.67500003409777.8359999952154752.53399999409548.453000009
2154657.19133836 409451.937813642154268.03610314409427.447408333
2154131.44600001409371.2109999952153855.22800003409327.340000018
2153666.33200002      409217.5442153623.32600002409149.125000015
2153590.60688317408952.1117724332153480.89127782408828.276561633
2152995.32684207408732.0796315072152876.34771889408573.763945311
2152749.90271319408256.3629817522152765.36228132407939.424763188
2152656.48173997407879.5308977512152410.29200001407825.621000022
2152312.42761424407740.6596365272152295.17700005407620.456000015
2152422.87099999407299.9330000132152407.42500003407190.613999993
2152317.74800001407130.3700000052152119.84699999407072.573000014
2152090.09442787406981.4611894492151955.77066374406941.643720359
2151842.86499999406864.2430000012151650.63500001406593.915000021
2151639.72600001406451.9260000142151735.09200001406356.511999995
2151763.19499999406220.5409999942151732.91968949406085.662080437

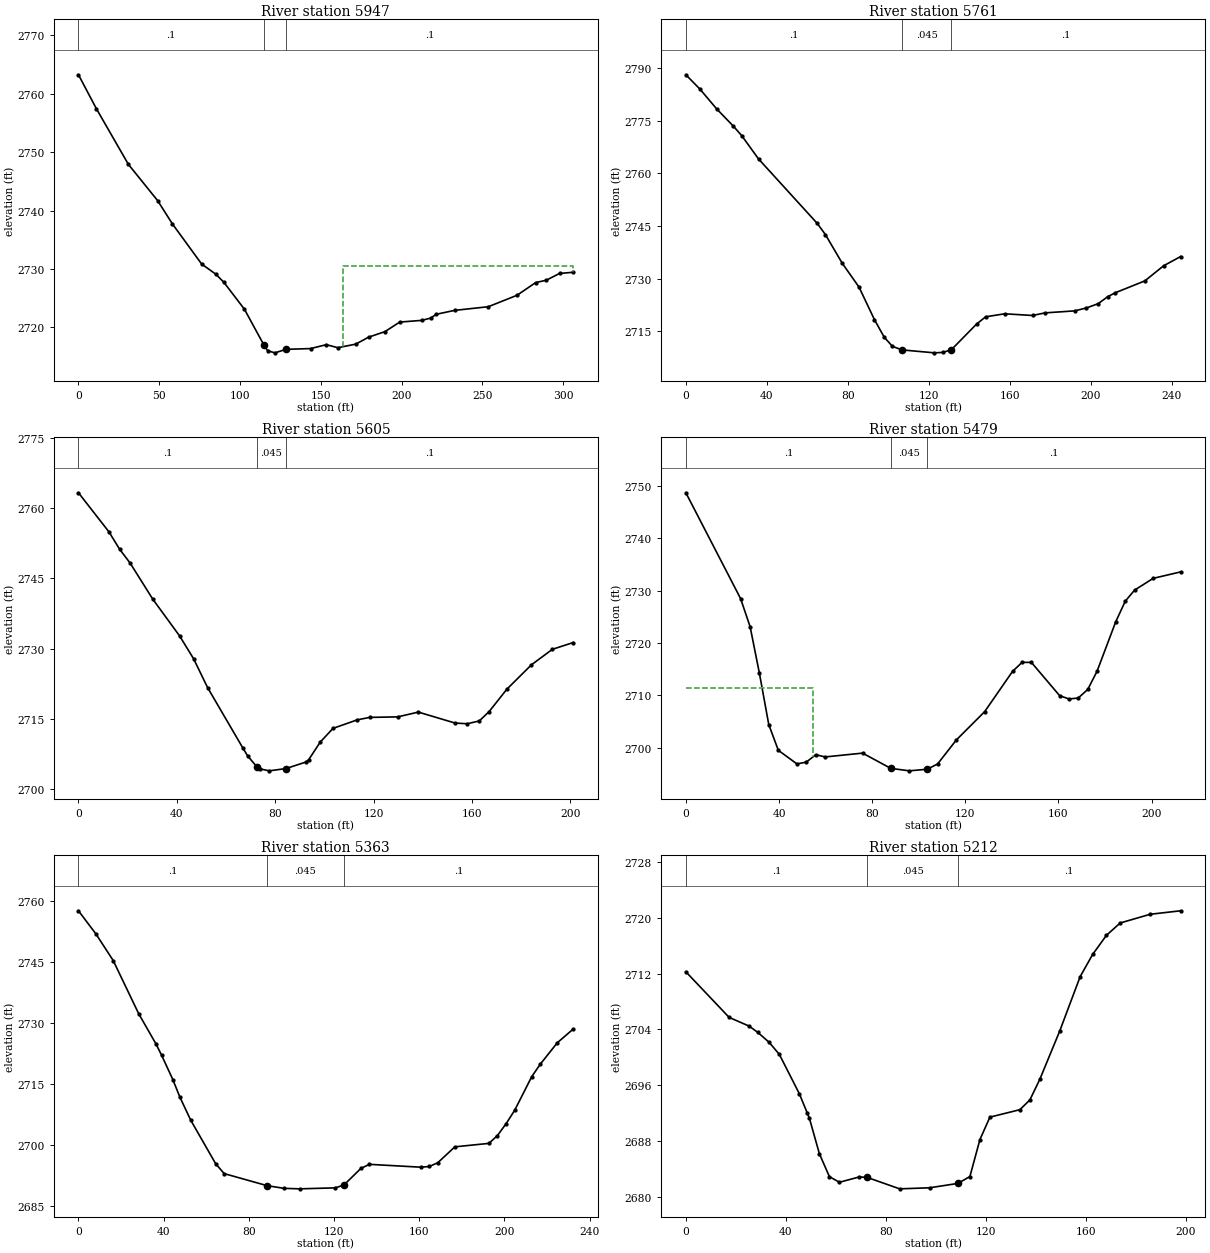
Type RM Length L Ch R = 1 ,5947    ,185.2,185.2,185.2
XS GIS Cut Line= 2
2154931.37551009409709.3625165642154661.49575892409854.018063191
#Sta/Elev= 30
       0 2763.25    11.1 2757.43    30.9  2747.9      49 2741.69    58.1 2737.72
    76.2 2730.84      85 2729.09    89.9 2727.73   102.7 2723.09   114.72716.989
   117.1 2715.97   121.6 2715.62   128.4 2716.22   143.6 2716.35   153.4 2717.02
   160.5  2716.5   171.6 2717.11   179.5  2718.3   189.7 2719.26   198.8 2720.89
   212.4 2721.18   217.9 2721.57   221.5 2722.23   232.7 2722.89   253.6 2723.52
   271.4 2725.48   282.9 2727.65   289.5 2728.06   297.7 2729.22   306.2 2729.42
#Mann= 3 ,-1,0
       0      .1       0   114.7    .045       0   128.4      .1       0
#XS Ineff= 2 , 0
                          163.98         2730.55
Permanent Ineff=
       F       F
Bank Sta=114.7,128.4
XS Rating Curve= 0 ,0
Exp/Cntr(USF)=0,0
Exp/Cntr=0.3,0.1

Type RM Length L Ch R = 1 ,5761    ,167.3,156,146.4
XS GIS Cut Line= 3
2154886.87328035409562.3544406862154749.85131124409598.071067703
2154660.88444031409649.373131964
#Sta/Elev= 30
       0 2788.03     6.9 2783.98    15.2 2778.33    23.5 2773.38    27.6 2770.69
    35.9 2764.07    64.8 2745.78    68.9 2742.56    77.2  2734.4    85.5 2727.61
    93.1 2718.36    97.9 2713.39     102 2710.74   106.82709.742   122.7 2708.91
   126.8 2709.03     1312709.747   143.5 2717.08     148 2719.16   157.4 2720.02
   171.2 2719.54   177.3 2720.28     192 2720.85   197.8 2721.69   203.6 2722.91
   208.2 2724.86   211.9 2725.98   226.6 2729.38   235.9 2733.69   244.3 2736.32
#Mann= 3 ,-1,0
       0      .1       0   106.8    .045       0     131      .1       0
Bank Sta=106.8,131
XS Rating Curve= 0 ,0
Exp/Cntr(USF)=0,0
Exp/Cntr=0.3,0.1

Type RM Length L Ch R = 1 ,5605    ,130,125.9,118.4
XS GIS Cut Line= 2
2154718.03104354409413.6433936522154599.19208456409575.991698275
#Sta/Elev= 30
       0 2763.26    12.4 2754.92    16.7 2751.24      21 2748.27    30.2 2740.58
    41.1 2732.74    46.8 2727.87    52.5 2721.71    66.8 2708.86    68.8 2707.12
    72.5 2704.84    73.8 2704.37    77.6 2703.95    84.4 2704.44    92.6 2705.85
    93.6 2706.32    98.3 2710.07   103.5 2713.01   113.4 2714.83   118.4 2715.35
   129.8 2715.46   138.2 2716.48   153.1 2714.15   158.1 2713.99     163  2714.6
     167  2716.6   174.2 2721.37   184.2 2726.57   192.7 2729.87   201.2 2731.32
#Mann= 3 ,-1,0
       0      .1       0    72.5    .045       0    84.4      .1       0
Bank Sta=72.5,84.4
XS Rating Curve= 0 ,0
Exp/Cntr(USF)=0,0
Exp/Cntr=0.3,0.1

Type RM Length L Ch R = 1 ,5479    ,115.7,116,113.9
XS GIS Cut Line= 2
 2154572.5669626409357.7955768622154547.89002029409568.848372871
#Sta/Elev= 30
       0 2748.65    23.5 2728.47    27.6 2723.09    31.6 2714.18    35.6 2704.44
    39.7 2699.53    47.7 2696.93    51.7 2697.27    55.8 2698.69    59.8 2698.26
    75.9 2698.99      88 2696.08      96 2695.61   103.7 2695.92   108.1 2696.92
   116.2 2701.52   128.3 2706.89   140.3 2714.58   144.4 2716.31   148.4 2716.29
   160.5 2709.96   164.5 2709.32   168.5  2709.5   172.6 2711.14   176.6 2714.62
   184.6 2724.03   188.7 2727.97   192.7 2730.08   200.7 2732.33   212.5 2733.56
#Mann= 3 ,-1,0
       0      .1       0      88    .045       0   103.7      .1       0
#XS Ineff= 2 , 0
           54.53 2711.44
Permanent Ineff=
       F       F
Bank Sta=88,103.7
XS Rating Curve= 0 ,0
Exp/Cntr(USF)=0,0
Exp/Cntr=0.3,0.1

Type RM Length L Ch R = 1 ,5363    ,149.8,151.2,149.6
XS GIS Cut Line= 2
2154460.36798225409328.9549895722154443.42975714409560.669909178
#Sta/Elev= 30
       0 2757.58     8.2 2751.87    16.3 2745.34    28.3 2732.21    36.3 2724.89
      39 2722.05    44.3 2716.03    47.6 2711.72    52.7 2706.03    64.4 2695.32
    68.4 2692.88    88.5 2689.92    96.5 2689.25   103.9 2689.13   120.5 2689.37
   124.6 2690.06   132.6 2694.16   136.6 2695.16   160.7 2694.46   164.7 2694.63
   168.7 2695.56   176.7 2699.47   192.7 2700.32   196.7 2702.25   200.8  2705.2
   204.8 2708.48   212.8 2716.75   216.8 2719.81   224.8 2725.09   232.3 2728.48
#Mann= 3 ,-1,0
       0      .1       0    88.5    .045       0   124.6      .1       0
Bank Sta=88.5,124.6
XS Rating Curve= 0 ,0
Exp/Cntr(USF)=0,0
Exp/Cntr=0.3,0.1

Type RM Length L Ch R = 1 ,5212    ,108.9,115.2,118.3
XS GIS Cut Line= 2
2154310.86149555409327.9234888122154296.57484474409525.339027232
#Sta/Elev= 30
       0 2712.25    17.3 2705.72    25.3 2704.47    28.7 2703.59    33.3 2702.15
    37.4 2700.41    45.4 2694.77    48.6 2691.98    49.4 2691.28    53.4 2686.19
    57.4 2682.91    61.4  2682.1    69.4 2682.87    72.62682.787    85.5 2681.16
    97.5 2681.31   108.82681.937   113.6 2682.92   117.6 2688.21   121.6 2691.43
   133.6  2692.5   137.6  2693.9   141.6 2696.88   149.5 2703.74   157.7 2711.56
   162.7 2714.74   168.2 2717.47   173.7 2719.24   185.7 2720.49   197.9 2720.99
#Mann= 3 ,-1,0
       0      .1       0    72.6    .045       0   108.8      .1       0
Bank Sta=72.6,108.8
XS Rating Curve= 0 ,0
Exp/Cntr(USF)=0,0
Exp/Cntr=0.3,0.1

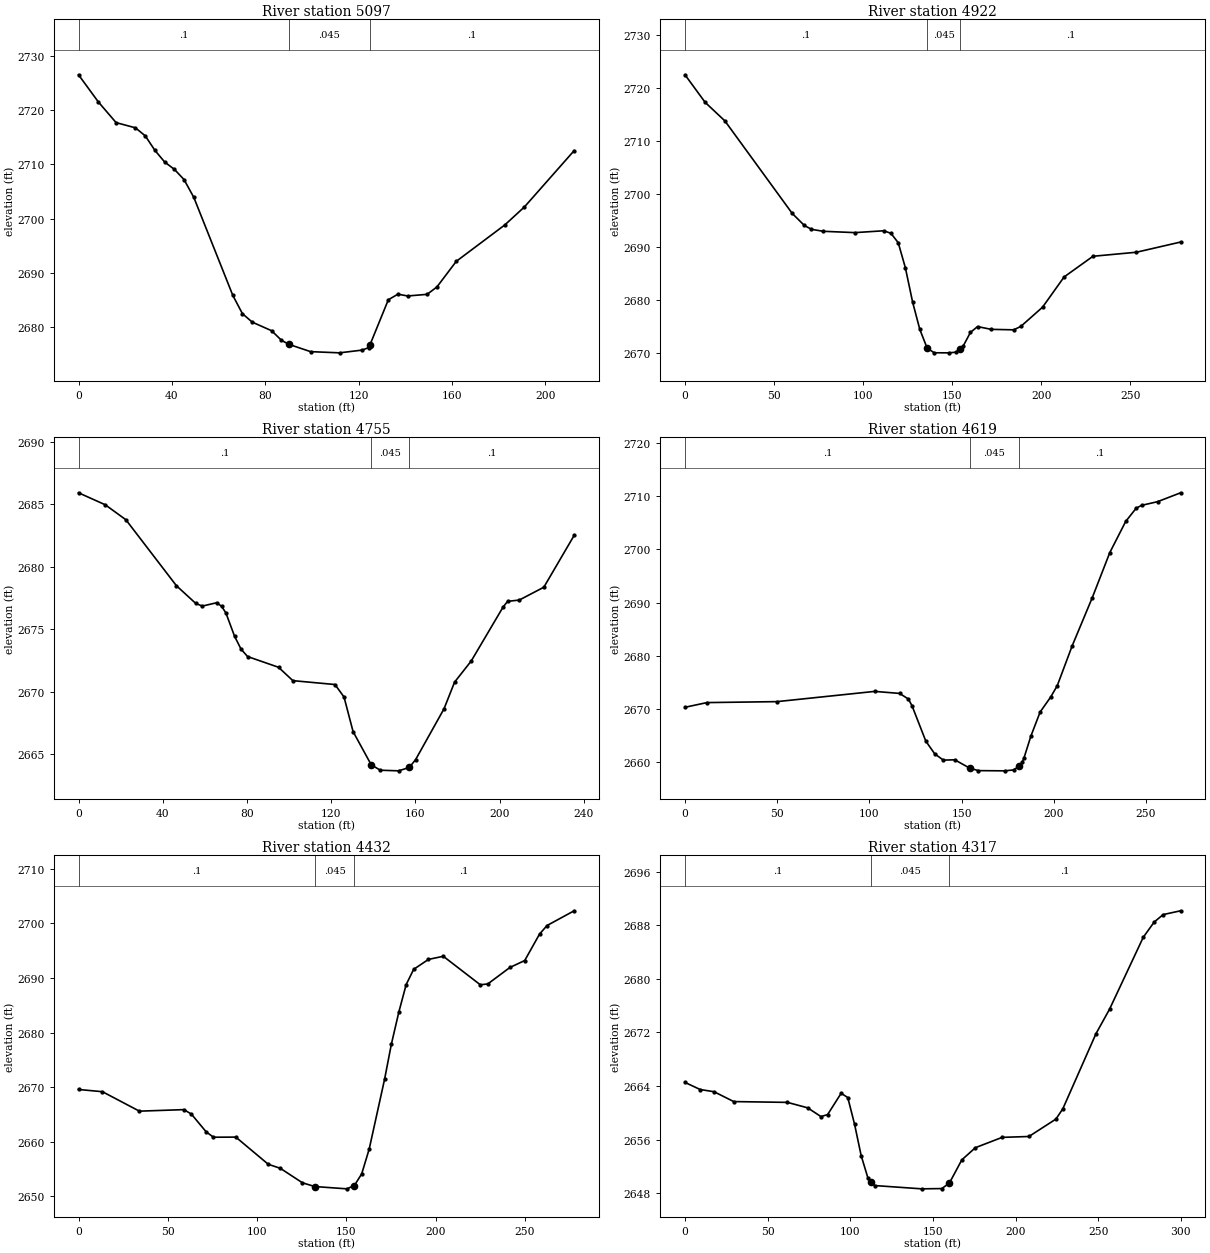
Type RM Length L Ch R = 1 ,5097    ,175.4,174.6,172.1
XS GIS Cut Line= 2
2154227.29800464409293.7234813272154168.35298123409497.659711741
#Sta/Elev= 30
       0 2726.47     8.5 2721.47    16.1 2717.67    24.4 2716.71    28.6 2715.23
    32.7 2712.58    36.9 2710.42    41.1 2709.06    45.2 2707.19    49.4  2703.9
    66.1 2685.88    70.2 2682.53    74.4 2680.97    82.7 2679.39    86.9 2677.64
    90.12676.881    99.4 2675.54   111.8 2675.32   121.6 2675.83   124.3  2676.3
   124.8 2676.75   132.7 2685.08   136.8 2686.11     141 2685.78   149.3 2686.08
   153.5 2687.43   161.8 2692.15   182.6 2698.85     191 2702.16   212.3 2712.52
#Mann= 3 ,-1,0
       0      .1       0    90.1    .045       0   124.8      .1       0
Bank Sta=90.1,124.8
XS Rating Curve= 0 ,0
Exp/Cntr(USF)=0,0
Exp/Cntr=0.3,0.1

Type RM Length L Ch R = 1 ,4922    ,163.6,167.9,170.1
XS GIS Cut Line= 2
2154055.00056746409211.032709484 2154010.8418286409485.726040905
#Sta/Elev= 30
       0 2722.44    11.3 2717.26    22.4 2713.76    60.2 2696.35      67 2694.09
      71 2693.36    77.6 2692.99    95.4 2692.74   111.6 2693.09   115.6 2692.61
   119.7 2690.84   123.7 2686.13   127.8 2679.62   131.8 2674.54   135.9 2671.02
   139.9 2670.13     148 2670.12   152.1 2670.24   154.4  2670.9   156.1 2671.36
   160.2 2673.95   164.2 2675.06   171.9 2674.54   184.5 2674.45   188.5 2675.09
   200.7 2678.71   212.8  2684.4     229 2688.29   253.4 2689.05   278.2 2690.97
#Mann= 3 ,-1,0
       0      .1       0   135.9    .045       0   154.4      .1       0
Bank Sta=135.9,154.4
XS Rating Curve= 0 ,0
Exp/Cntr(USF)=0,0
Exp/Cntr=0.3,0.1

Type RM Length L Ch R = 1 ,4755    ,132.5,135.7,139.3
XS GIS Cut Line= 2
2153923.82313733409188.3039468362153835.50565961409406.500068249
#Sta/Elev= 30
       0 2685.93    12.7 2684.97    22.5 2683.77    46.5 2678.49    55.7 2677.07
    58.8 2676.86    65.7 2677.13      68 2676.83      70 2676.31    74.1 2674.45
    77.2 2673.41    80.3 2672.82      95 2671.96   101.8 2670.89   121.8 2670.58
   126.1 2669.58   130.4 2666.81     139 2664.16   143.3 2663.72     152 2663.67
   157.1 2663.94   160.1 2664.57   173.6 2668.64   178.6 2670.77   186.5 2672.46
   201.6 2676.77   203.8 2677.24   209.3 2677.34     221 2678.37   235.4 2682.52
#Mann= 3 ,-1,0
       0      .1       0     139    .045       0   157.1      .1       0
Bank Sta=139,157.1
XS Rating Curve= 0 ,0
Exp/Cntr(USF)=0,0
Exp/Cntr=0.3,0.1

Type RM Length L Ch R = 1 ,4619    ,175.3,186.5,199.9
XS GIS Cut Line= 2
 2153832.2985949409135.1816942282153687.30738789409361.476381797
#Sta/Elev= 30
       0 2670.35    11.9 2671.23    49.9 2671.41   102.9 2673.33   116.4 2672.95
   121.1 2671.91   123.1 2670.66   130.6 2664.01   135.4 2661.63   140.1 2660.44
   146.3  2660.5   154.4 2658.94   159.1 2658.47   173.4 2658.43   178.2  2658.6
   181.1 2659.29   182.9 2660.05   183.9  2660.9   187.6 2664.95   192.6 2669.46
   198.4 2672.31   201.9 2674.41     210 2681.89   220.9 2690.92   230.4 2699.37
     239  2705.2   244.7 2707.69   247.6 2708.22   256.3 2708.91   268.8 2710.58
#Mann= 3 ,-1,0
       0      .1       0   154.4    .045       0   181.1      .1       0
Bank Sta=154.4,181.1
XS Rating Curve= 0 ,0
Exp/Cntr(USF)=0,0
Exp/Cntr=0.3,0.1

Type RM Length L Ch R = 1 ,4432    ,117.4,115.7,117.5
XS GIS Cut Line= 2
2153757.09287538409103.3378310072153489.46891852409177.188492519
#Sta/Elev= 30
       0 2669.59    13.4 2669.18    34.1 2665.62      59  2665.9    63.2 2665.09
    71.5 2661.83    75.6 2660.85    88.1 2660.87   106.3 2655.89     113 2655.16
   125.4 2652.51   132.3 2651.82   150.3  2651.4   154.5 2652.01   158.6 2654.14
   162.8 2658.68   171.4 2671.43   175.2 2677.85   179.4 2683.76   183.5 2688.78
   187.7 2691.58     196  2693.4   204.3 2693.97     225 2688.76   229.2  2688.9
   241.6 2691.92   249.9 2693.19   258.2 2698.03   262.4  2699.6   277.6  2702.3
#Mann= 3 ,-1,0
       0      .1       0   132.3    .045       0   154.5      .1       0
Bank Sta=132.3,154.5
XS Rating Curve= 0 ,0
Exp/Cntr(USF)=0,0
Exp/Cntr=0.3,0.1

Type RM Length L Ch R = 1 ,4317    ,181,164.1,151.4
XS GIS Cut Line= 2
2153745.24000224 409001.928093132153449.76608783409053.230157391
#Sta/Elev= 30
       0 2664.55     9.2 2663.49    17.6 2663.16    29.5 2661.69      62 2661.57
    74.2 2660.76    82.3 2659.45    86.3 2659.75    94.5 2662.93    98.5 2662.29
   102.6 2658.32   106.6 2653.63   110.7 2650.28   112.5 2649.74   114.8 2649.16
   143.2 2648.67   155.4 2648.71     1602649.536   167.5 2652.99   175.7 2654.81
   191.9 2656.35   208.1 2656.48   224.4 2659.07   228.6  2660.6   248.7 2671.83
   256.9 2675.48   277.3 2686.21   283.9 2688.48   289.3 2689.59   299.9 2690.16
#Mann= 3 ,-1,0
       0      .1       0   112.5    .045       0     160      .1       0
Bank Sta=112.5,160
XS Rating Curve= 0 ,0
Exp/Cntr(USF)=0,0
Exp/Cntr=0.3,0.1

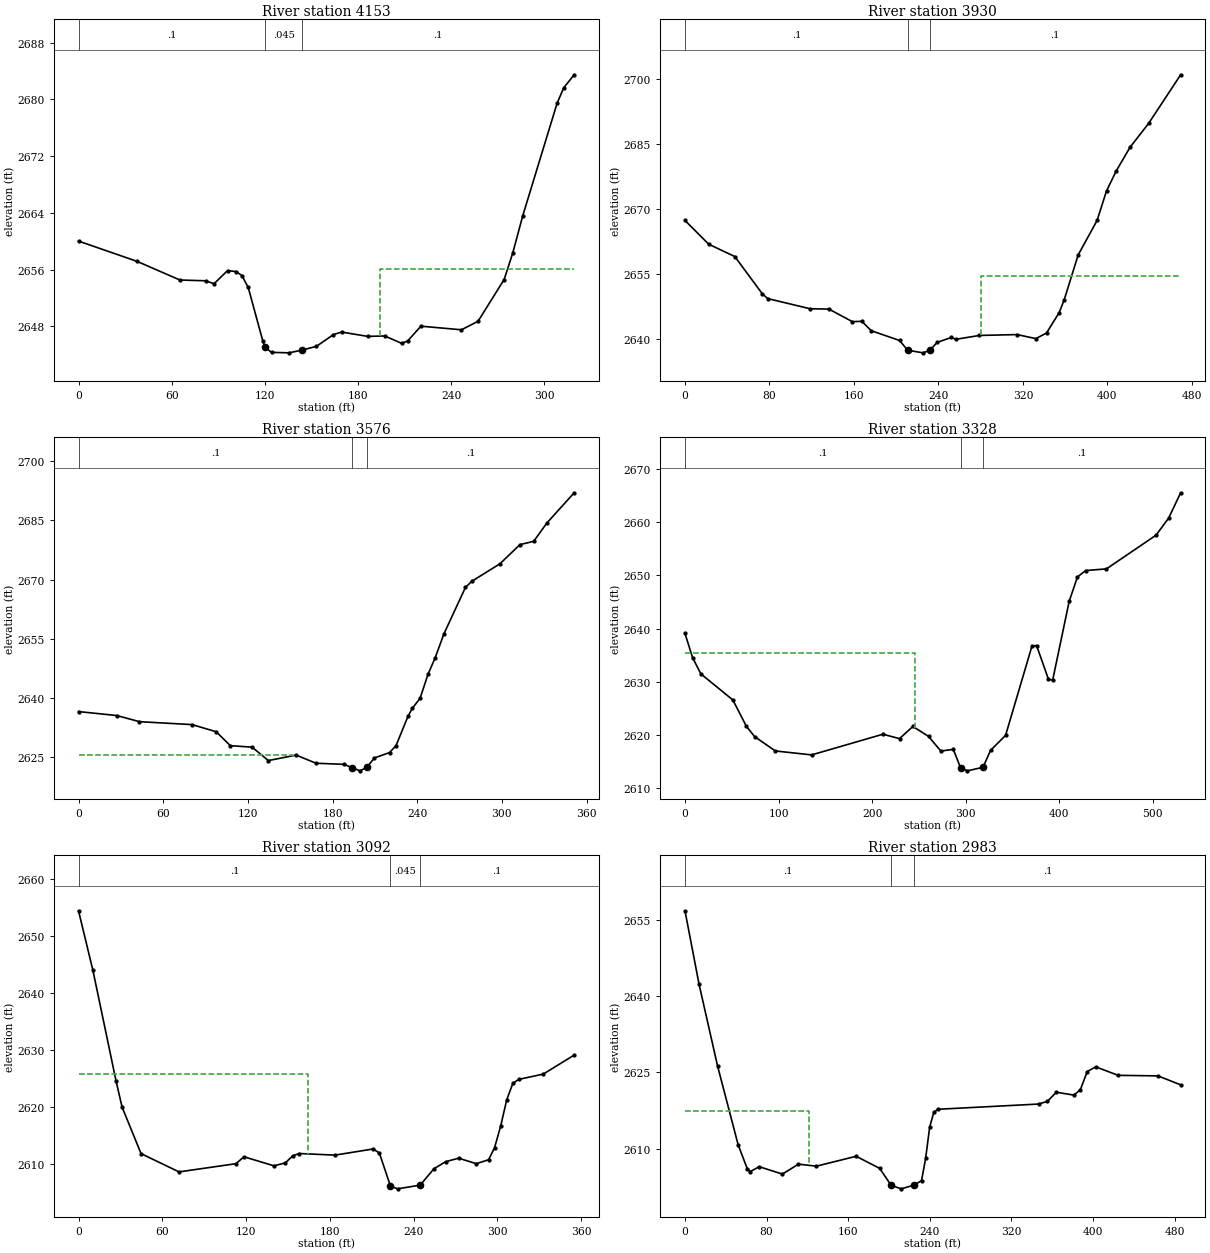
Type RM Length L Ch R = 1 ,4153    ,226.1,222,215.3
XS GIS Cut Line= 2
2153624.29719045408789.6419018322153405.45532194409022.034350443
#Sta/Elev= 30
       0 2660.01    37.8 2657.14    65.3 2654.52    81.8 2654.41    87.3    2654
      96 2655.85   101.6  2655.7   105.2 2655.15   109.3 2653.47   118.6 2645.99
   120.2 2645.02   124.3 2644.32   135.6 2644.25   144.1 2644.65   153.2 2645.16
   164.2 2646.83   169.5 2647.18   186.2 2646.57   197.2 2646.63   208.2 2645.58
     212 2645.93   220.5 2648.01   246.6  2647.5   257.3  2648.7   274.1 2654.59
   279.6 2658.29   286.1 2663.59   308.2 2679.44   312.5 2681.64   319.2 2683.46
#Mann= 3 ,-1,0
       0      .1       0   120.2    .045       0   144.1      .1       0
#XS Ineff= 2 , 0
                          194.09         2656.02
Permanent Ineff=
       F       F
Bank Sta=120.2,144.1
XS Rating Curve= 0 ,0
Exp/Cntr(USF)=0,0
Exp/Cntr=0.3,0.1

Type RM Length L Ch R = 1 ,3930    ,352.5,354.5,355.1
XS GIS Cut Line= 2
2153435.94412715408610.7742445922153229.29778072409032.197285514
#Sta/Elev= 30
       0 2667.27    22.5 2661.79    47.2 2658.95    73.4 2650.31    78.4 2649.26
   118.5 2646.91   136.3 2646.84   158.6 2643.93   167.5 2644.02   176.4 2641.85
   203.2  2639.6   210.9 2637.35   225.4 2636.75   231.8 2637.31   238.8 2639.16
   252.2 2640.29   256.6 2639.88   278.9 2640.76   314.5 2640.96   332.3 2640.03
   342.4 2641.32   354.4 2646.04   359.1 2648.95   372.4 2659.35   390.3 2667.28
   399.2 2674.08   408.3 2678.63   421.4 2684.12   439.3 2689.72   469.4 2700.86
#Mann= 3 ,-1,0
       0      .1       0   210.9    .045       0   231.8      .1       0
#XS Ineff= 2 , 0
                          280.34         2654.46
Permanent Ineff=
       F       F
Bank Sta=210.9,231.8
XS Rating Curve= 0 ,0
Exp/Cntr(USF)=0,0
Exp/Cntr=0.3,0.1

Type RM Length L Ch R = 1 ,3576    ,243.6,248.2,254.4
XS GIS Cut Line= 2
2153129.70101703408585.028142413 2152895.2759814408846.554338227
#Sta/Elev= 30
       0 2636.46    27.1 2635.46    43.2  2633.9    80.5 2633.15    97.5 2631.35
   107.6  2627.8     123 2627.43   134.5 2624.02   154.2 2625.41   168.3 2623.34
   188.1 2623.06   194.1 2622.18   199.5 2621.41   204.3 2622.32   209.7 2624.69
   220.4 2626.05     225 2627.83   233.5  2635.3   236.6 2637.34     242 2639.82
   247.6 2645.89   252.7 2650.12     259 2656.28   274.2 2668.02   278.8 2669.59
   298.6    2674   312.8 2678.88   322.5  2679.7   331.9 2684.38   351.2 2692.04
#Mann= 3 ,-1,0
       0      .1       0   194.1    .045       0   204.3      .1       0
#XS Ineff= 2 , 0
          152.28 2625.38
Permanent Ineff=
       F       F
Bank Sta=194.1,204.3
XS Rating Curve= 0 ,0
Exp/Cntr(USF)=0,0
Exp/Cntr=0.3,0.1

Type RM Length L Ch R = 1 ,3328    ,235.5,236,237.1
XS GIS Cut Line= 2
2153131.54214866408400.3375152732152652.38735795408626.490315195
#Sta/Elev= 30
       0 2639.07     8.1 2634.53      17 2631.46    51.2 2626.55    65.6 2621.61
    74.5 2619.65    96.6 2616.96   135.4 2616.22   211.6 2620.11   229.3 2619.28
   243.6 2621.57   260.3 2619.71   273.5 2616.94   286.8 2617.26   294.6 2613.78
   301.9 2613.22   318.62613.893   326.6 2617.06   342.7  2619.9   370.8 2636.65
   375.8  2636.8   388.5 2630.46     393 2630.28   410.7 2645.14   419.5  2649.7
   428.3 2650.91   450.5 2651.22   503.5 2657.56     517 2660.78   529.8 2665.54
#Mann= 3 ,-1,0
       0      .1       0   294.6    .045       0   318.6      .1       0
#XS Ineff= 2 , 0
          245.87 2635.47
Permanent Ineff=
       F       F
Bank Sta=294.6,318.6
XS Rating Curve= 0 ,0
Exp/Cntr(USF)=0,0
Exp/Cntr=0.3,0.1

Type RM Length L Ch R = 1 ,3092    ,103.6,109.1,114.7
XS GIS Cut Line= 3
2152983.68443764408204.3256107772152825.46226995 408288.65281004
2152663.76269198408357.331663048
#Sta/Elev= 30
       0 2654.43    10.3    2644    26.9 2624.59    31.2 2620.03    44.8 2611.87
      72 2608.67   112.8 2610.11   118.5 2611.32     140 2609.73   148.1 2610.25
   153.6 2611.51   158.1 2611.89   183.7 2611.61   211.1 2612.69   215.5 2611.97
   223.4 2606.18   228.5  2605.7   244.7 2606.35   254.6 2609.23     263 2610.46
   272.2 2611.07     285 2610.11   293.7  2610.8     298 2612.92   302.4 2616.73
   306.7 2621.31   311.1  2624.2   315.4 2624.89   332.8  2625.8     355 2629.14
#Mann= 3 ,-1,0
       0      .1       0   223.4    .045       0   244.7      .1       0
#XS Ineff= 2 , 0
           164.2 2625.74
Permanent Ineff=
       F       F
Bank Sta=223.4,244.7
XS Rating Curve= 0 ,0
Exp/Cntr(USF)=0,0
Exp/Cntr=0.3,0.1

Type RM Length L Ch R = 1 ,2983    ,311.8,300.7,287.4
XS GIS Cut Line= 4
2152932.30051806408126.6735179882152787.13310652408204.755989347
2152692.55433839408210.2547549362152483.60124602408297.135251236
#Sta/Elev= 30
       0 2656.85    13.8 2642.37    31.9  2626.3    52.1 2610.74      61 2606.05
      64 2605.46    72.8 2606.41    95.5 2604.96   111.2 2606.91   128.9 2606.52
   167.8 2608.47   190.8 2606.09   202.1 2602.76   211.9 2602.05   224.8  2602.8
   231.9 2603.67   235.9 2608.03   239.9 2614.25   243.9 2617.11   247.9 2617.73
   346.6 2618.76   355.3 2619.29     364 2621.09   381.3 2620.52   387.6 2621.58
   394.3 2625.15   402.6  2626.1   424.6 2624.42   463.6 2624.31   485.9 2622.55
#Mann= 3 ,-1,0
       0      .1       0   202.1    .045       0   224.8      .1       0
#XS Ineff= 2 , 0
          121.14  2617.4
Permanent Ineff=
       F       F
Bank Sta=202.1,224.8
XS Rating Curve= 0 ,0
Exp/Cntr(USF)=0,0
Exp/Cntr=0.3,0.1

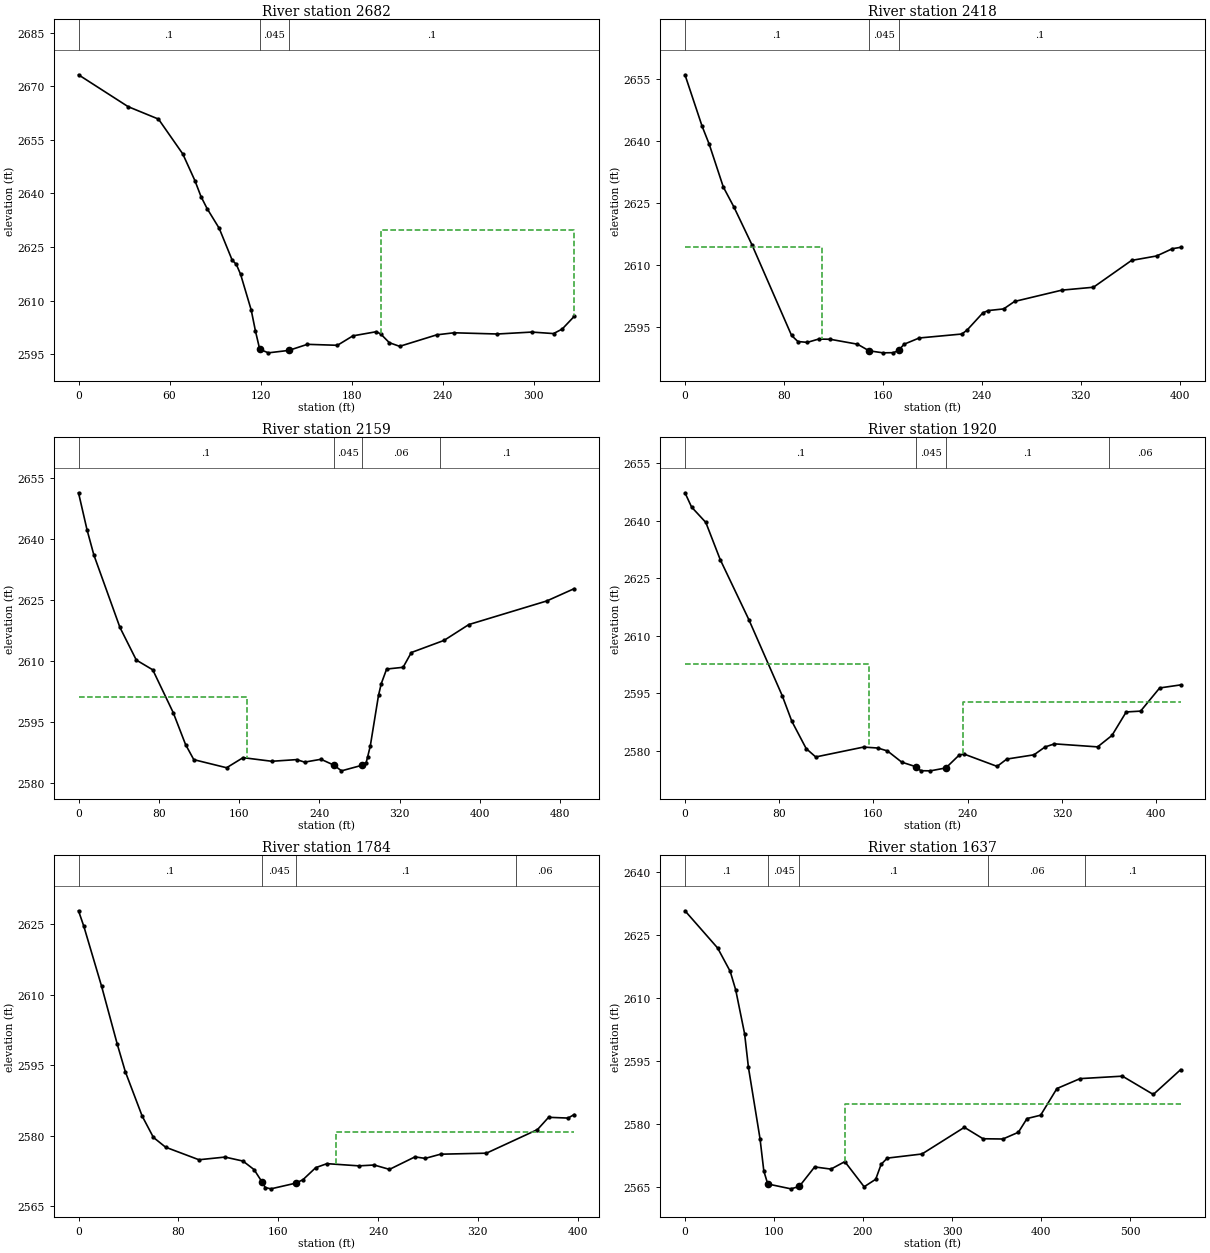
Type RM Length L Ch R = 1 ,2682    ,267.2,264.2,258.6
XS GIS Cut Line= 3
 2152860.8165654407895.7253632642152759.63927857407899.024622618
 2152618.8708795408074.985121455
#Sta/Elev= 30
       0 2673.18    32.7 2664.26    52.7 2660.78    68.7 2651.04    76.7 2643.57
    80.7 2639.12    84.7 2635.77    92.7 2630.23   101.2 2621.38     104 2620.12
   106.8 2617.36   113.8 2607.36   116.6 2601.47   119.4 2596.38   125.1 2595.39
   138.62596.072   150.8 2597.77   170.6  2597.5   180.8 2600.14   196.2  2601.3
   199.1 2600.68   204.8 2598.23   211.6 2597.21   236.1 2600.43   247.4    2601
     276 2600.66   298.7  2601.2     313 2600.78   318.7 2602.04   326.6 2605.58
#Mann= 3 ,-1,0
       0      .1       0   119.4    .045       0   138.6      .1       0
#XS Ineff= 2 , 0
                          199.28         2629.85
Permanent Ineff=
       F       F
Bank Sta=119.4,138.6
XS Rating Curve= 0 ,0
Exp/Cntr(USF)=0,0
Exp/Cntr=0.3,0.1

Type RM Length L Ch R = 1 ,2418    ,239.1,258.6,276.5
XS GIS Cut Line= 4
2152591.90893804407733.5639028262152526.93426824407781.391180009
2152507.85020541407814.4928170112152411.52515643408079.386701706
#Sta/Elev= 30
       0 2655.94    13.8 2643.54    19.6 2639.15      31 2628.81    39.6 2623.96
    54.3 2614.75    86.2 2592.92    91.3 2591.46    98.9 2591.25   108.1 2592.05
   117.4    2592   139.5 2590.81148.82652589.218   160.1 2588.72   168.6 2588.76
172.82652589.329   177.1 2590.79   189.4 2592.31   223.9 2593.27   228.2 2594.25
   240.9 2598.39   245.2 2598.94   257.7 2599.34   266.5 2601.14   304.8 2603.88
   330.3 2604.58   361.1 2611.06   381.4 2612.14   394.1 2613.89   400.8 2614.23
#Mann= 3 ,-1,0
       0      .1       0148.8265    .045       0172.8265      .1       0
#XS Ineff= 2 , 0
          111.07  2614.2
Permanent Ineff=
       F       F
Bank Sta=148.8265,172.8265
XS Rating Curve= 0 ,0
Exp/Cntr(USF)=0,0
Exp/Cntr=0.3,0.1

Type RM Length L Ch R = 1 ,2159    ,231.9,238.9,246.7
XS GIS Cut Line= 2
2152564.51199893407647.3405261342152081.47020919407750.748299304
#Sta/Elev= 30
       0 2651.41     8.5  2642.3    15.3 2636.13    41.3 2618.32    57.6 2610.31
      74 2607.91    94.4 2597.39   106.7 2589.55   114.9 2585.84   147.6 2583.85
     164 2586.33   192.6 2585.44   217.5 2585.85   225.3 2585.23   241.7 2585.93
   254.5 2584.49   262.1 2583.09   282.6 2584.46   286.7 2585.13   288.2 2586.55
   290.8 2589.19     299 2601.64   301.7 2604.49   307.1  2608.1   323.5 2608.53
   331.7 2612.16   364.4 2615.15     389 2619.03   466.7 2624.83     494 2627.85
#Mann= 4 ,-1,0
       0      .1       0   254.5    .045       0   282.6     .06       0
     360      .1       0
#XS Ineff= 2 , 0
           168.2 2601.22
Permanent Ineff=
       F       F
Bank Sta=254.5,282.6
XS Rating Curve= 0 ,0
Exp/Cntr(USF)=0,0
Exp/Cntr=0.3,0.1

Type RM Length L Ch R = 1 ,1920    ,130.9,136.4,141.9
XS GIS Cut Line= 2
2152561.67890926 407512.768766532152146.63127174407443.358069471
#Sta/Elev= 30
       0  2647.3     5.6 2643.58    17.7 2639.56    29.9 2629.88    54.2 2614.22
    82.6 2594.34    90.7  2587.7   102.9 2580.56     111 2578.38   151.6 2580.96
   163.7 2580.71   171.9 2579.95     184 2577.03   196.2 2575.82   200.2 2574.79
   208.4 2574.76   221.5 2575.52   232.7 2578.85   236.7 2579.16     265 2575.92
   273.2 2577.83   296.3 2578.94   305.7 2580.99   313.7  2581.8   350.3 2581.01
   362.5 2583.99   374.6 2590.12   386.8 2590.34     403 2596.38   420.8 2597.18
#Mann= 4 ,-1,0
       0      .1       0   196.2    .045       0   221.5      .1       0
     360     .06       0
#XS Ineff= 2 , 0
          156.36 2602.66   235.8         2592.72
Permanent Ineff=
       F       F
Bank Sta=196.2,221.5
XS Rating Curve= 0 ,0
Exp/Cntr(USF)=0,0
Exp/Cntr=0.3,0.1

Type RM Length L Ch R = 1 ,1784    ,164.5,147.2,127.6
XS GIS Cut Line= 3
2152537.63144014407421.5433846032152349.80835408407326.021929411
2152167.35164192407364.659821399
#Sta/Elev= 30
       0 2627.83     4.3 2624.49    18.5 2611.76    31.1  2599.4    37.5  2593.6
      51 2584.15      60 2579.61    69.8 2577.52    96.5 2574.85   117.4 2575.42
   131.8 2574.57   140.7 2572.75   147.1 2570.11   149.7 2568.93   154.2 2568.66
   173.9 2569.86   179.8 2570.59   190.1 2573.17   199.1 2574.02   224.7 2573.55
   236.9 2573.73   249.2  2572.8   269.6 2575.46   277.8 2575.14   290.1 2576.03
   326.9 2576.25   367.8 2581.27   376.7 2583.88   392.3 2583.72   397.2 2584.47
#Mann= 4 ,-1,0
       0      .1       0   147.1    .045       0   173.9      .1       0
  350.72     .06       0
#XS Ineff= 2 , 0
                          206.42         2580.71
Permanent Ineff=
       F       F
Bank Sta=147.1,173.9
XS Rating Curve= 0 ,0
Exp/Cntr(USF)=0,0
Exp/Cntr=0.3,0.1

Type RM Length L Ch R = 1 ,1637    ,210.6,194,179.9
XS GIS Cut Line= 2
2152522.01565379 407168.548370912152007.80987762407382.446641439
#Sta/Elev= 30
       0 2630.77    36.7  2621.9    50.8 2616.34      57 2611.92      67 2601.47
    71.3 2593.46    84.3 2576.51    88.6 2568.77      93  2565.7     119 2564.54
   128.4  2565.1   145.7 2569.76     164 2569.24   179.6 2571.02   201.3 2565.03
   214.3 2566.82   220.4 2570.38   227.3 2571.86   266.3 2572.84   313.9 2579.19
   334.9 2576.47   357.2 2576.41   374.6 2578.01   384.3 2581.28   399.6 2582.08
   417.9 2588.43   443.9 2590.79   491.5 2591.38   526.2 2587.02   556.9 2592.93
#Mann= 5 ,-1,0
       0      .1       0      93    .045       0   128.4      .1       0
     340     .06       0     450      .1       0
#XS Ineff= 2 , 0
                          179.44         2584.85
Permanent Ineff=
       F       F
Bank Sta=93,128.4
XS Rating Curve= 0 ,0
Exp/Cntr(USF)=0,0
Exp/Cntr=0.3,0.1

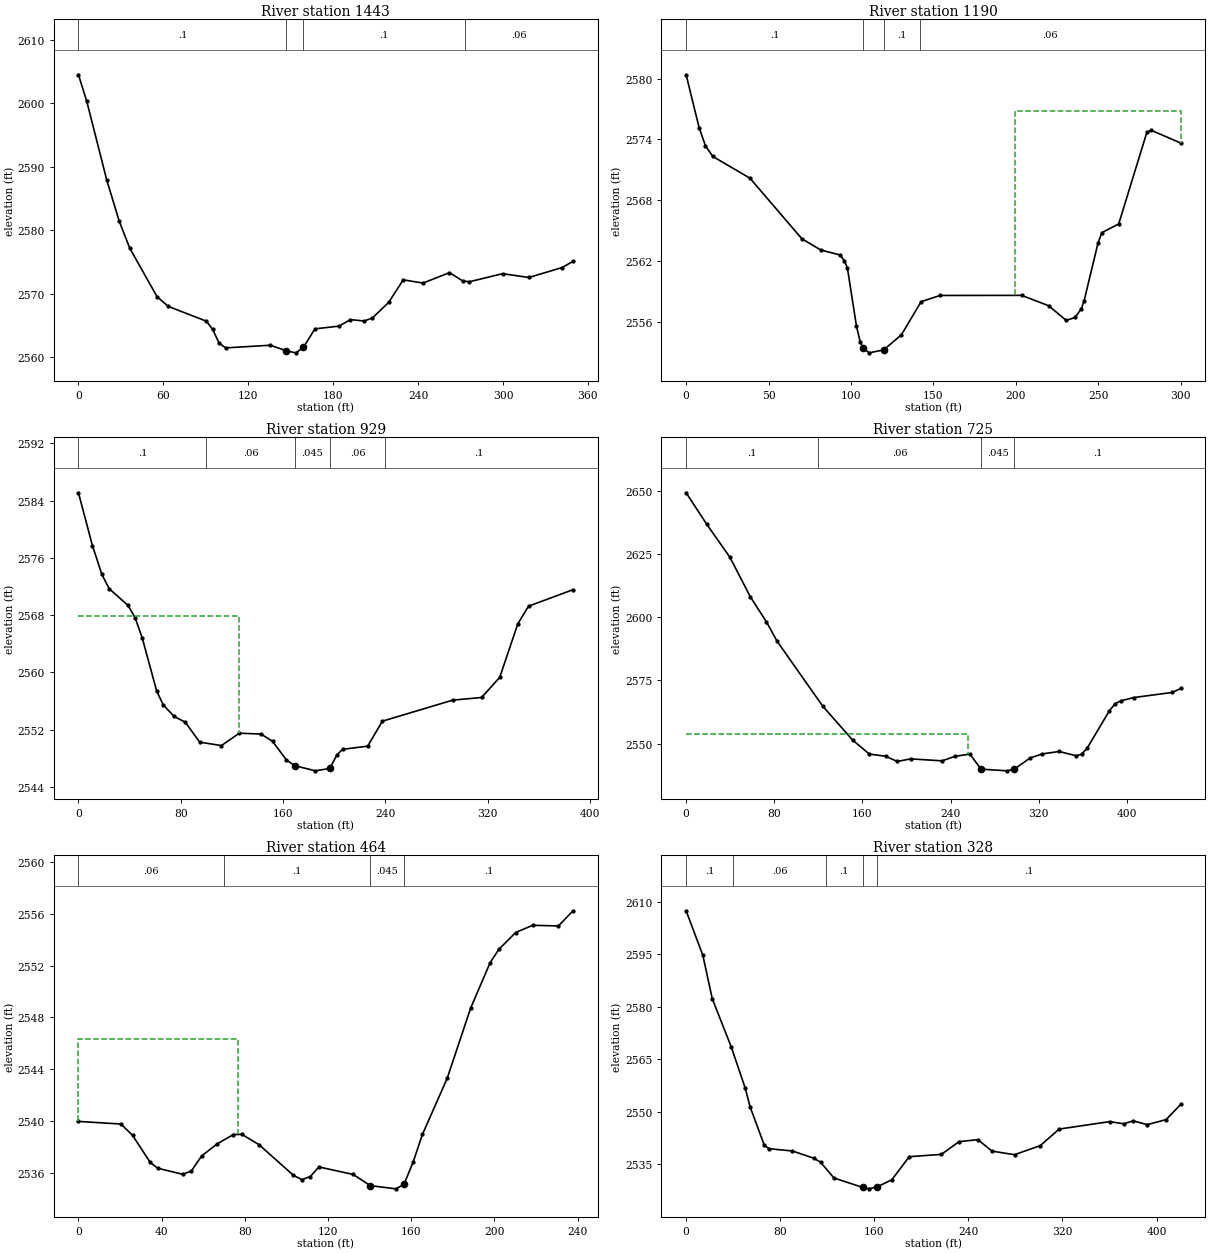
Type RM Length L Ch R = 1 ,1443    ,252.2,252.9,251.2
XS GIS Cut Line= 4
2152330.87951588406976.9749165692152250.22487814407131.855199179
2152253.14714762407149.9732699752152171.90805599407283.813212306
#Sta/Elev= 30
       0 2604.52     5.9 2600.31    19.9    2588    28.8 2581.44    36.3 2577.16
    55.5 2569.55    63.4 2568.01    90.4 2565.67    94.9 2564.36    99.4  2562.2
     104 2561.46   135.6 2561.88   146.82561.012   153.6 2560.68     159 2561.54
   167.1 2564.46   184.1 2564.89   192.2 2565.92   201.8  2565.7   207.7 2566.17
   219.3 2568.65   229.5 2572.19   243.5 2571.68   262.2 2573.32   271.6 2572.01
   276.3 2571.89   299.7 2573.16   318.3 2572.56   341.8 2574.13   349.5  2575.1
#Mann= 4 ,-1,0
       0      .1       0   146.8    .045       0     159      .1       0
  272.97     .06       0
Bank Sta=146.8,159
XS Rating Curve= 0 ,0
Exp/Cntr(USF)=0,0
Exp/Cntr=0.3,0.1

Type RM Length L Ch R = 1 ,1190    ,253,260.5,265.6
XS GIS Cut Line= 4
2152170.52512852406912.8162849832152098.08658645406950.461511568
2152067.28594652407018.3369958662151970.32096895 407124.42808897
#Sta/Elev= 30
       0 2580.37     7.9 2575.14    11.7 2573.37    16.2 2572.31    38.7 2570.17
    70.2 2564.19    81.6 2563.09    93.4 2562.59    95.9 2562.02    97.8 2561.31
   103.3 2555.56   105.6    2554   107.4  2553.4     111 2552.94   119.8 2553.23
   130.5 2554.71   142.5 2557.99     154  2558.6   203.4 2558.61   219.8 2557.59
   230.5 2556.14   235.9 2556.43   239.7 2557.31   241.3 2558.05   249.7 2563.73
   252.1  2564.8   262.3 2565.65   279.4  2574.7   282.1 2574.89   299.9 2573.64
#Mann= 4 ,-1,0
       0      .1       0   107.4    .045       0   119.8      .1       0
  141.64     .06       0
#XS Ineff= 2 , 0
                          199.67         2576.81
Permanent Ineff=
       F       F
Bank Sta=107.4,119.8
XS Rating Curve= 0 ,0
Exp/Cntr(USF)=0,0
Exp/Cntr=0.3,0.1

Type RM Length L Ch R = 1 ,929     ,199.8,203.8,204.8
XS GIS Cut Line= 2
2151982.26835002406737.3905962992151711.99159494407014.041803148
#Sta/Elev= 30
       0 2585.09    10.9 2577.72    18.3 2573.69      24 2571.69    38.8 2569.34
    44.4  2567.6      50 2564.73    61.2 2557.37    66.4 2555.42    74.9 2553.83
    83.6 2553.02    94.8 2550.24   111.8 2549.76   125.8 2551.49   142.8 2551.37
   151.8 2550.36   162.6 2547.76     169 2546.97   185.2 2546.23   196.5 2546.56
   202.2 2548.47   206.6 2549.24   226.2 2549.68   237.7 2553.17   292.7 2556.11
   315.3 2556.48   329.5  2559.3   343.6 2566.76     352 2569.24   386.8 2571.55
#Mann= 5 ,-1,0
       0      .1       0     100     .06       0     169    .045       0
   196.5     .06       0     240      .1       0
#XS Ineff= 2 , 0
          125.63 2567.93
Permanent Ineff=
       F       F
Bank Sta=169,196.5
XS Rating Curve= 0 ,0
Exp/Cntr(USF)=0,0
Exp/Cntr=0.3,0.1

Type RM Length L Ch R = 1 ,725     ,249.2,261.1,274.1
XS GIS Cut Line= 2
2151955.49565258406538.5077010522151601.07613413406813.884017547
#Sta/Elev= 30
       0 2649.22    18.5  2636.9    39.7 2623.74    58.4 2607.98    72.7 2598.31
    82.6 2590.49     124 2564.83   151.1 2551.43   166.3  2545.9     181 2545.03
   191.6 2542.98   203.8    2544   232.3 2543.22   243.7 2544.97   257.5  2545.9
   267.6 2539.95   291.2 2539.27   297.7 2539.91   312.1 2544.34   323.3 2545.98
   338.5 2546.92   353.7 2545.26   358.8  2545.8   363.9 2548.22   384.1 2563.02
   389.2 2565.76   394.2 2566.91   406.2 2568.25   441.2 2570.27   448.8 2571.84
#Mann= 4 ,-1,0
       0      .1       0     120     .06       0   267.6    .045       0
   297.7      .1       0
#XS Ineff= 2 , 0
          255.77 2553.93
Permanent Ineff=
       F       F
Bank Sta=267.6,297.7
XS Rating Curve= 0 ,0
Exp/Cntr(USF)=0,0
Exp/Cntr=0.3,0.1

Type RM Length L Ch R = 1 ,464     ,130.6,136.8,138.5
XS GIS Cut Line= 3
2151781.89011728406487.7927291192151707.63545504406498.611289181
2151549.29107596406460.746328965
#Sta/Elev= 30
       0 2539.98    20.4 2539.78      26 2538.91    34.5 2536.82    38.1 2536.37
    50.2  2535.9    54.3 2536.16    59.2 2537.31    66.6 2538.24    74.5 2538.97
    78.6 2538.98    86.8 2538.19   103.3 2535.83   107.4 2535.49   111.5 2535.73
   115.6 2536.47   132.1 2535.89   140.3 2535.03   152.6 2534.78   156.52535.118
   160.9 2536.83   165.4 2538.98   177.3 2543.31   188.6 2548.73   197.9 2552.21
   202.1 2553.25   210.2 2554.55   218.4 2555.11   230.8 2555.06   237.8 2556.23
#Mann= 4 ,-1,0
       0     .06       0      70      .1       0   140.3    .045       0
   156.5      .1       0
#XS Ineff= 2 , 0
           76.92 2546.33
Permanent Ineff=
       F       F
Bank Sta=140.3,156.5
XS Rating Curve= 0 ,0
Exp/Cntr(USF)=0,0
Exp/Cntr=0.3,0.1

Type RM Length L Ch R = 1 ,328     ,105.7,96.6,85.8
XS GIS Cut Line= 4
2151858.41095222406415.156794559 2151749.7638951406411.322192543
2151673.92398857406356.3595636492151455.77774056406355.933496758
#Sta/Elev= 30
       0  2607.5    14.2 2594.77    22.2 2582.39    38.3 2568.62    50.3 2556.72
    54.3 2551.53    66.3  2540.6    70.3 2539.47    90.3 2538.82   108.5 2536.76
   114.3  2535.6   125.7 2531.09   150.2 2528.39   155.1 2527.99   162.42528.536
   174.9 2530.59   189.7 2537.18     217 2537.84   232.1 2541.49   248.1 2542.05
   260.1 2538.77   279.2 2537.75   301.1 2540.35   317.2 2545.08   360.1 2547.21
   372.1 2546.59   380.1 2547.44   392.1 2546.34   408.1 2547.79   420.5 2552.13
#Mann= 5 ,-1,0
       0      .1       0      40     .06       0  118.71      .1       0
   150.2    .045       0   162.4      .1       0
Bank Sta=150.2,162.4
XS Rating Curve= 0 ,0
Exp/Cntr(USF)=0,0
Exp/Cntr=0.3,0.1