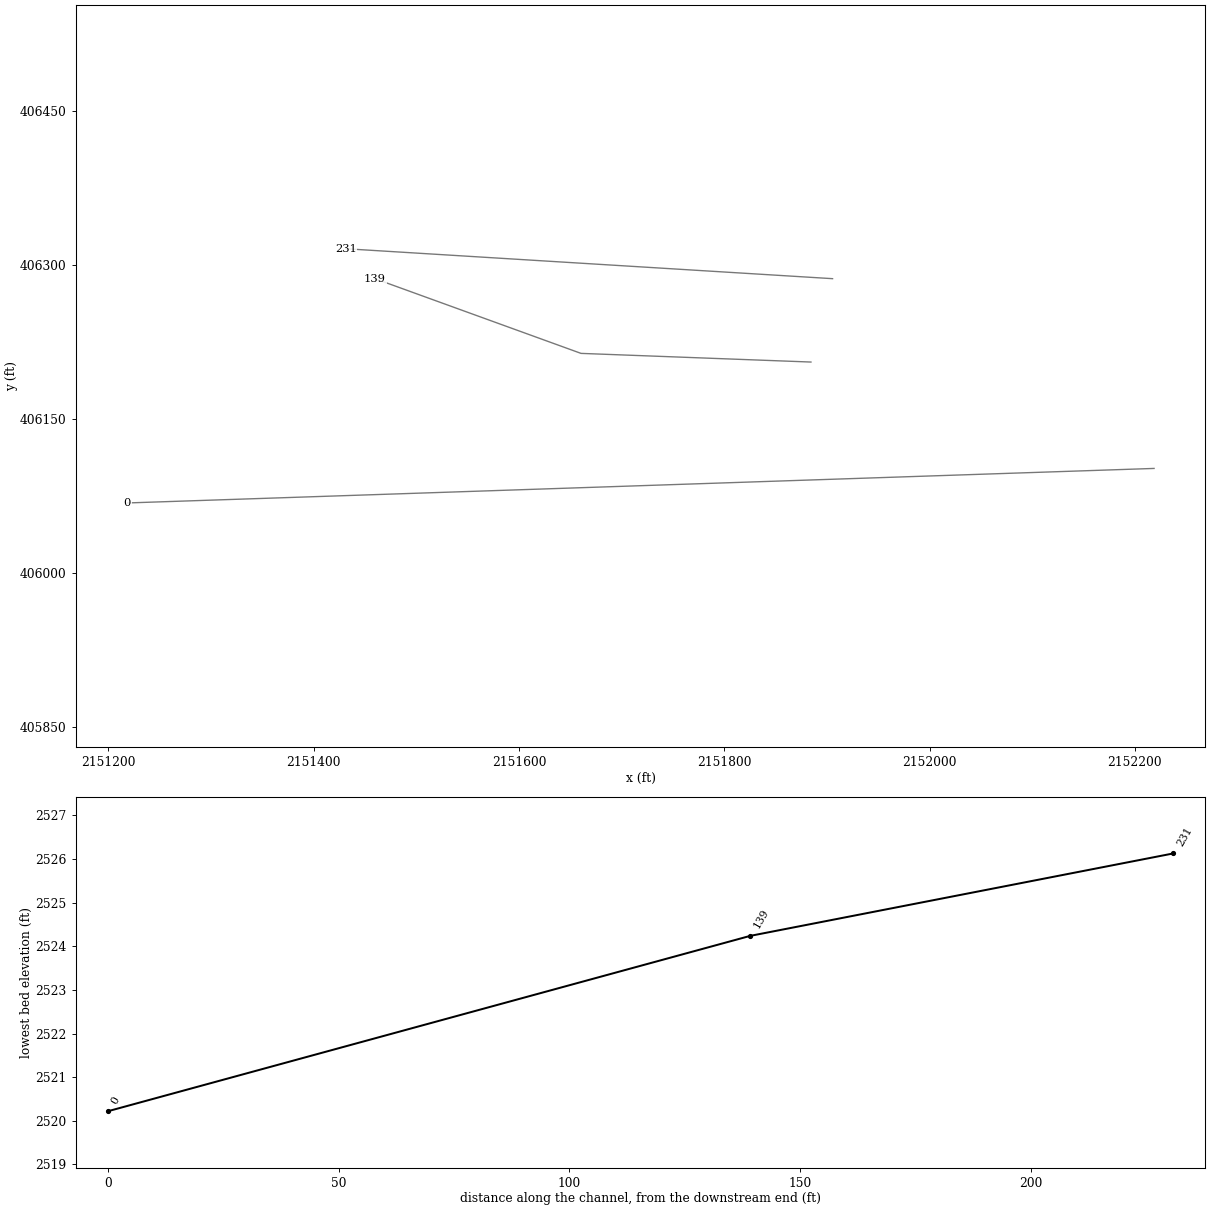
HEC-RAS study RBBNSRN.prj: RBBNSRN

--- RBBNSRN.g01 (geometry) --- (continued)

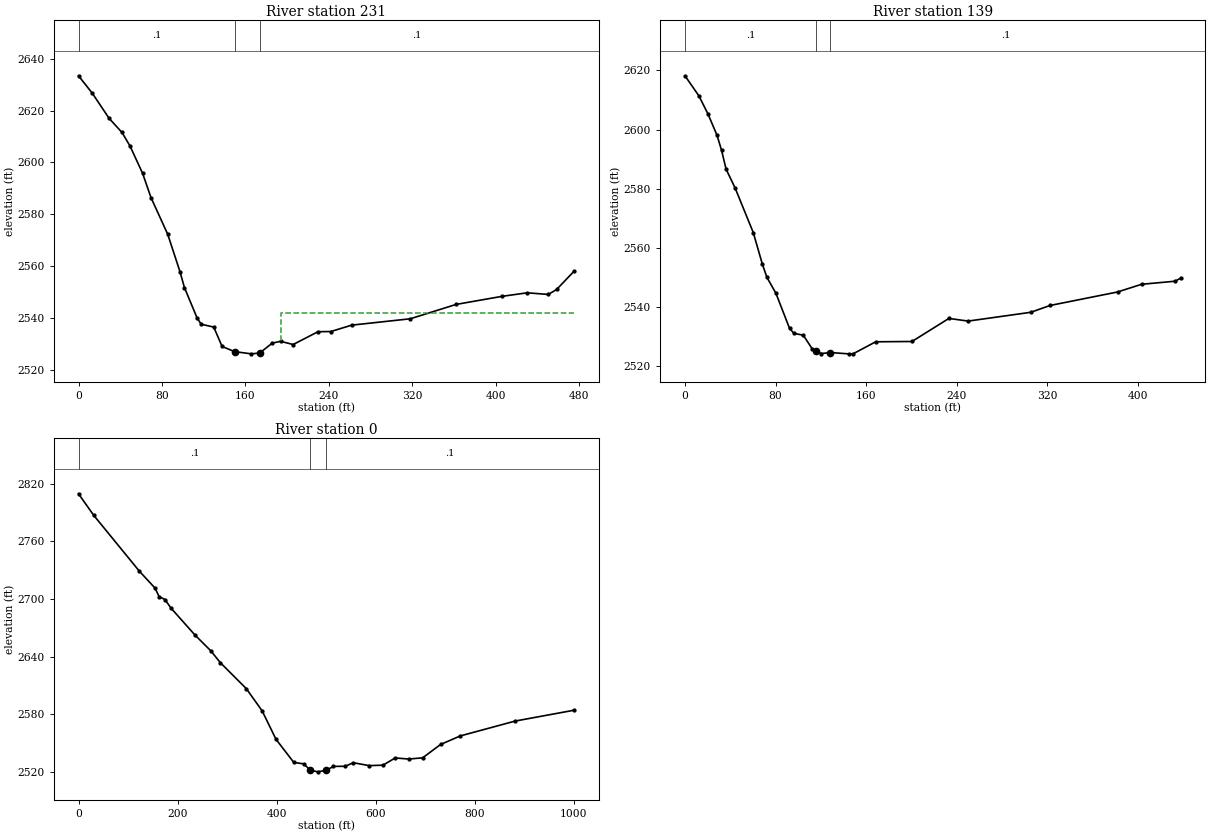
Type RM Length L Ch R = 1 ,231     ,88.3,91.7,92.1
XS GIS Cut Line= 2
 2151905.4945345406286.8844514332151431.36978765406316.031464559
#Sta/Elev= 30
       0 2633.47    13.3 2626.68    29.4 2616.99    41.7 2611.58    49.4 2606.32
    61.4 2595.82    69.5  2586.4    85.5 2572.28    97.2 2557.89   101.5 2551.72
   113.5 2540.11   117.5 2537.56   129.6 2536.46   137.6 2528.98   149.6 2526.98
   165.5 2526.13   173.6 2526.43   185.7 2530.28   193.7 2530.95   205.7 2529.73
   229.5 2534.67   241.8 2534.74   261.8 2537.21   317.9 2539.66   361.9 2545.21
   406.1 2548.34     430 2549.69   450.2 2549.06   458.2 2550.98     475 2558.07
#Mann= 3 ,-1,0
       0      .1       0   149.6    .045       0   173.6      .1       0
#XS Ineff= 2 , 0
                           194.1         2542.01
Permanent Ineff=
       F       F
Bank Sta=149.6,173.6
XS Rating Curve= 0 ,0
Exp/Cntr(USF)=0,0
Exp/Cntr=0.3,0.1

Type RM Length L Ch R = 1 ,139     ,132.1,139.2,135.3
XS GIS Cut Line= 3
 2151884.4521398406205.6479309272151660.41147942406214.090042767
 2151459.7489749406286.822083238
#Sta/Elev= 30
       0 2618.15    12.3 2611.36    20.3 2605.26    28.3 2598.04    32.3 2592.97
    36.3 2586.61    44.3 2580.22    60.3 2565.19    68.3 2554.56    72.3  2550.1
    80.3 2544.69    92.3 2532.85    96.3 2531.13   104.4 2530.55   112.4 2525.89
   115.5  2525.1   120.4 2524.34   128.4 2524.67   144.4 2524.24   148.4 2524.25
   168.4 2528.31   200.4 2528.41     233  2536.2     250  2535.3   305.3 2538.27
   322.3 2540.57   381.9 2545.13   403.1 2547.73   432.8 2548.77   437.6 2549.82
#Mann= 3 ,-1,0
       0      .1       0   115.5    .045       0   128.4      .1       0
Bank Sta=115.5,128.4
XS Rating Curve= 0 ,0
Exp/Cntr(USF)=0,0
Exp/Cntr=0.3,0.1

Type RM Length L Ch R = 1 ,0       ,502,508,507.4
XS GIS Cut Line= 2
 2152218.7456703406101.9969135672151218.31164755 406068.35951364
#Sta/Elev= 30
       0 2809.57    30.6 2787.24   122.6 2729.21   154.7 2711.31   162.7 2702.62
   174.7 2699.48   186.7 2690.65   234.7 2662.86   266.9 2646.29   286.7  2633.7
   338.8 2606.84   370.8 2583.72   398.8 2554.11   434.8    2530   454.8 2528.55
  467.792522.169   482.8 2520.22   500.5 2521.88   514.9 2525.89   538.9 2526.01
   554.9 2529.74   586.9 2526.67   614.9 2527.16   639.6 2534.67   666.9 2533.54
     695  2534.8   731.2 2548.69     771 2557.59   882.2  2573.1    1001 2584.36
#Mann= 3 ,-1,0
       0      .1       0  467.79    .045       0   500.5      .1       0
Bank Sta=467.79,500.5
XS Rating Curve= 0 ,0
Exp/Cntr=0.3,0.1
LCMann Table=0

Chan Stop Cuts=-1
Use User Specified Reach Order=0
Composite Channel Slope=5